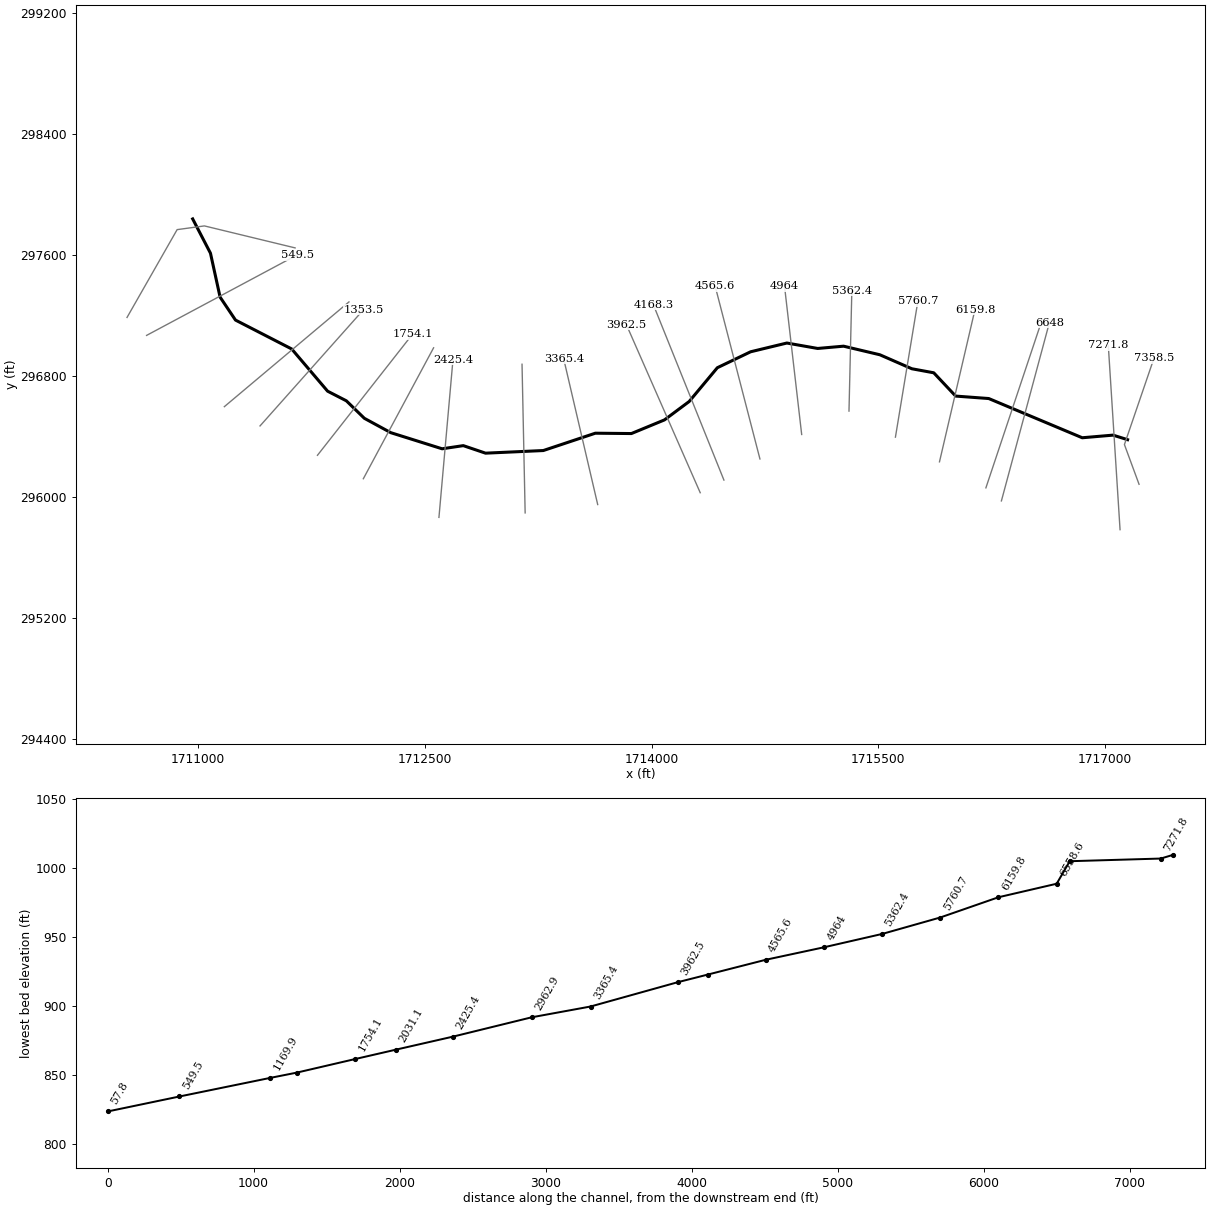
--- SLABFRK.prj (project) ---

Proj Title=SLABFRK
Current Plan=p01
Default Exp/Contr=0,0
English Units
Geom File=g01
Flow File=f01
Plan File=p01
BEGIN DESCRIPTION:
END DESCRIPTION:
DSS Export Rating Curves= 0
DSS Export Rating Curve Sorted= 0
DSS Export Volume Flow Curves= 0
DXF OffsetX= 0
DXF OffsetY= 0
DXF ScaleX= 0
DXF ScaleY= 0

--- SLABFRK.p01 (plan) ---

Plan Title=Floodplain
Program Version=4.00
Geom File=g01
Flow File=f01
K Sum by GR=0
Std Step Tol=0.01
Critical Tol=0.01
Num of Std Step Trials=20
Max Error Tol=0.3
Flow Tol Ratio=0.001
Split Flow NTrial=30
Split Flow Tol=0.02
Split Flow Ratio=0.02
Log Output Level=0
Friction Slope Method=1
Unsteady Friction Slope Method=2
Unsteady Bridges Friction Slope Method=1
Global Log Level=0
CheckData=False
Run HTab=0
Run UNet=0
Run PostProcess=0
UNET Theta=0
UNET Theta Warmup=0
UNET ZTol=0
UNET ZSATol=0
UNET MxIter=0
UNET MaxInSteps=0
UNET DtIC=0
UNET DtMin=0
UNET MaxCRTS=0
UNET WFStab=0
UNET SFStab=0
UNET WFX=0
UNET SFX=0
UNET DSS MLevel=0
UNET DZMax Abort=0
UNET Convert EG Bridges=0
UNET Use Existing IB Tables=0
UNET Froude Limit=0
UNET Froude Power=0
Write IC File=0
Echo Input=False
Echo Output=False
Write Detailed=0

--- SLABFRK.f01 (steady flow) ---

Flow Title=NFF Regression Equation
Program Version=4.00
Number of Profiles=1
Profile Names=P100yr
River Rch & RM=SLABFRK,Main      ,7358.5
927.2205
River Rch & RM=SLABFRK,Main      ,3365.4
1024.549
River Rch & RM=SLABFRK,Main      ,3365.4
1253.091
River Rch & RM=SLABFRK,Main      ,57.8
1357.539
Boundary for River Rch & Prof#=SLABFRK,Main      ,1
Up Type=0
Dn Type=3
Dn Slope=0.017331

--- SLABFRK.g01 (geometry) ---

Geom Title=USGS 10m DEM
Program Version=4.10

River Reach=SLABFRK         ,Main
Reach XY= 30
     1717148.336      296380.756     1717052.206      296410.869
     1716848.362      296393.496     1716229.881      296652.934
     1716010.981      296669.149     1715866.206       296823.19
      1715721.43      296849.829     1715509.479      296942.485
     1715269.731      296999.237     1715098.317       296984.18
     1714894.473      297020.084     1714654.725      296962.174
     1714434.666      296856.778     1714248.196      296633.245
     1714084.889      296511.633     1713865.989      296421.293
     1713627.399       296423.61     1713283.413      296308.948
     1712901.206      296291.575     1712754.114      296341.377
     1712613.971       296320.53     1712274.618      296427.084
     1712099.729      296522.057     1711980.434      296637.877
     1711856.506      296701.578     1711619.075      296980.706
     1711247.291      297171.809      1711145.37      297323.534
     1711081.668      297614.243     1710963.986      297841.005

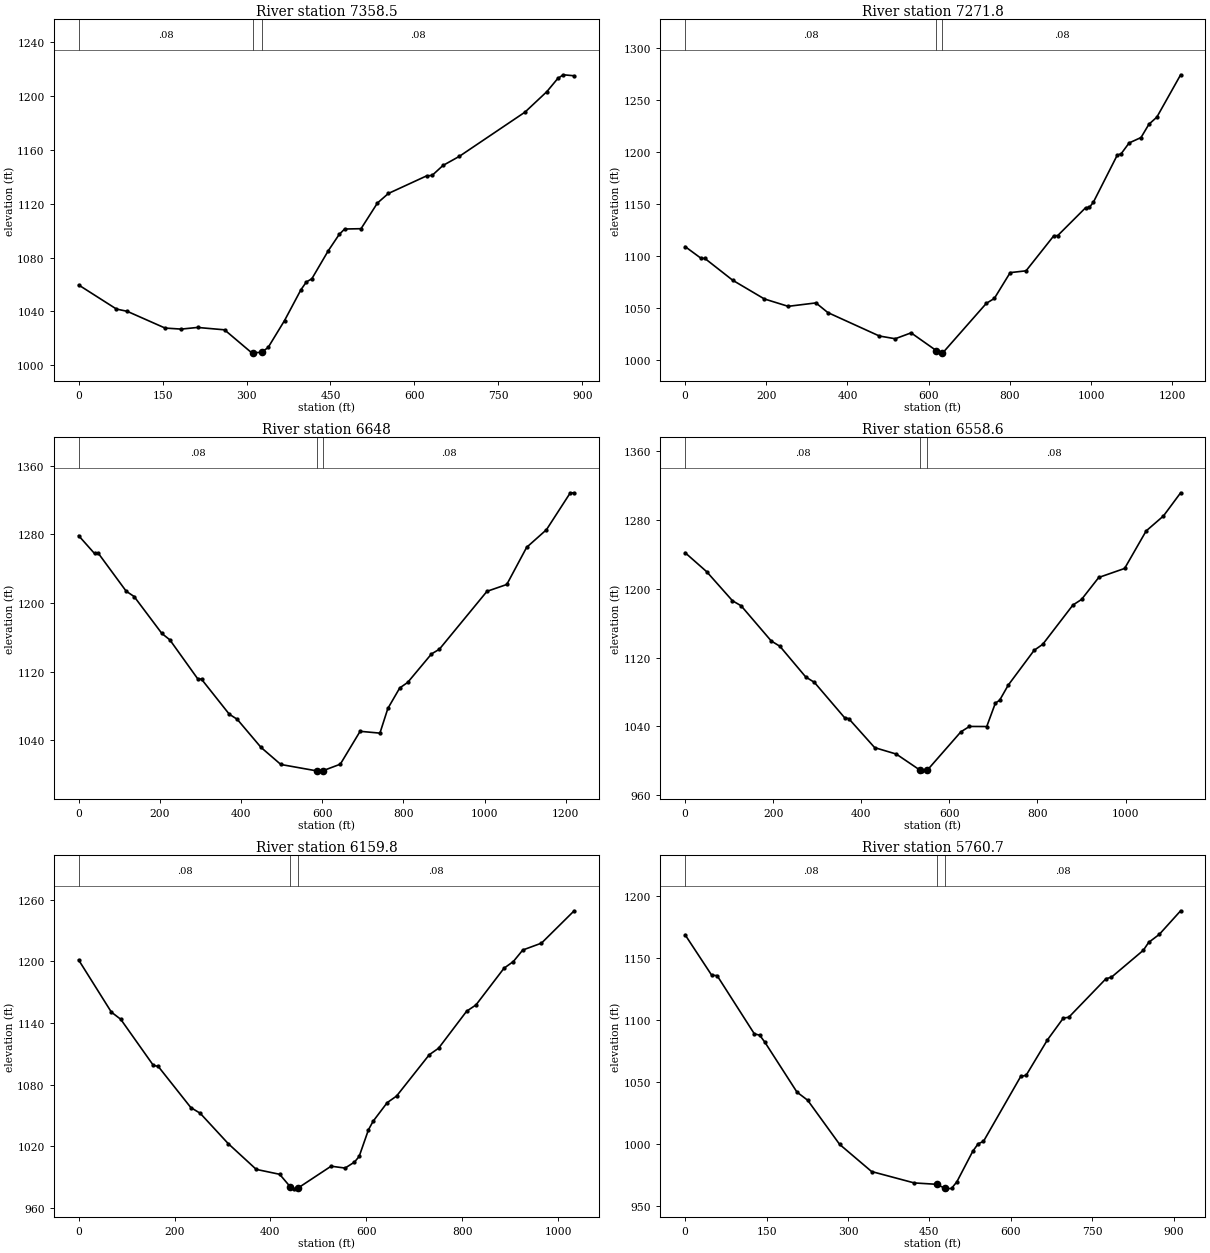
Type RM Length L Ch R = 1 ,7358.5  ,77.8,86.7,95.5
XS GIS Cut Line= 3
      1717224.17      296085.745     1717127.395      296348.476
     1717323.493      296921.252
#Sta/Elev= 30
       0 1059.65    67.6 1041.79    86.9  1040.1   154.5  1027.7   183.4 1026.93
   212.4 1028.16   260.7  1026.4   309.3 1009.34     312 1009.35     327 1009.75
   338.6 1013.33   367.9 1033.28   397.2 1056.11   406.9 1061.88   416.7 1064.25
     446 1084.98   465.5 1097.07   475.3 1101.11   504.6 1101.35   533.9 1120.39
   553.4 1127.45   621.8 1140.51   631.5 1140.82     651 1148.21   680.3 1154.99
   797.5 1187.74   836.6 1202.94   856.1 1212.69   865.9 1215.43   885.4 1214.69
#Mann= 3 , 0 , 0
       0     .08       0     312    .045       0     327     .08       0
Bank Sta=312,327
XS Rating Curve= 0 ,0
Exp/Cntr=0.3,0.1

Type RM Length L Ch R = 1 ,7271.8  ,631.2,623.8,616.4
XS GIS Cut Line= 2
     1717098.519      295785.595     1717020.795      297003.855
#Sta/Elev= 30
       0 1108.96    39.1 1097.73    48.8  1097.5   117.2 1076.55   195.3  1058.5
   253.9 1051.39   322.3 1054.69   351.6 1045.38   478.5  1022.8   517.6 1020.16
   556.7 1025.83   618.6 1008.79   633.6 1006.62   634.8 1006.58   742.2 1054.33
   761.7 1058.96   800.8 1083.87   839.9 1085.61   908.2 1119.34     918  1119.6
   986.4 1146.32   996.1 1146.75  1005.9 1151.85  1064.5 1197.03  1074.2 1198.44
  1093.8 1208.81  1123.1 1214.04  1142.6 1226.85  1162.1 1233.69  1220.7  1274.5
#Mann= 3 , 0 , 0
       0     .08       0   618.6    .045       0   633.6     .08       0
Bank Sta=618.6,633.6
XS Rating Curve= 0 ,0
Exp/Cntr=0.3,0.1

Type RM Length L Ch R = 1 ,6648    ,90.8,89.4,88.1
XS GIS Cut Line= 2
      1716313.67      295975.712     1716630.955      297154.495
#Sta/Elev= 30
       0 1278.61    39.1 1257.84    48.8 1257.88   117.2 1213.88   136.7 1207.71
   205.1 1164.64   224.6 1157.28     293 1112.09   302.7 1111.41   371.1 1070.62
   390.6 1064.73   449.2 1031.99   498.1 1012.06     586 1004.65   586.8 1004.65
   601.8 1004.78   644.6  1012.4   693.4  1050.7   742.2 1048.57   761.7 1077.29
     791 1101.21   810.6 1107.64   869.2 1140.82   888.7 1146.34  1005.9 1213.76
  1054.7 1221.74  1103.6 1264.99  1152.4 1285.52    1211  1328.4  1220.7 1328.56
#Mann= 3 , 0 , 0
       0     .08       0   586.8    .045       0   601.8     .08       0
Bank Sta=586.8,601.8
XS Rating Curve= 0 ,0
Exp/Cntr=0.3,0.1

Type RM Length L Ch R = 1 ,6558.6  ,396.5,398.7,401
XS GIS Cut Line= 2
     1716211.087      296062.112      1716567.68        297129.1
#Sta/Elev= 30
       0 1242.04    48.9 1219.99   107.6 1186.11   127.2  1180.3   195.6 1139.36
   215.2 1133.22   273.9  1097.5   293.5 1091.26     362  1050.2   371.7 1048.96
   430.4 1015.34   479.4 1007.86   534.2  988.85     538  988.35   549.2  988.75
   626.1 1033.72   645.6 1039.97   684.8 1039.87   704.4 1067.11   714.1 1070.46
   733.7  1088.1   792.4 1128.51     812 1135.52   880.4 1181.14     900 1187.66
   939.1 1213.23   997.8  1223.7  1046.7 1267.34  1085.9 1284.71    1125 1311.71
#Mann= 3 , 0 , 0
       0     .08       0   534.2    .045       0   549.2     .08       0
Bank Sta=534.2,549.2
XS Rating Curve= 0 ,0
Exp/Cntr=0.3,0.1

Type RM Length L Ch R = 1 ,6159.8  ,397,399.2,401.4
XS GIS Cut Line= 2
     1715904.051      296234.238     1716138.759      297240.845
#Sta/Elev= 30
       0 1201.33    68.3 1150.53    87.8  1143.6     156 1098.62   165.8 1097.84
     234 1057.68   253.5 1052.14     312 1022.58   370.5   997.5   419.3  992.72
   441.8  980.32   448.6  978.57   456.8  979.11   526.6  1000.6   555.8  998.78
   575.3 1004.58   585.1  1010.1   604.6 1036.14   614.3 1044.39   643.6 1062.45
   663.1 1068.84   731.3 1109.05   750.8 1115.43   809.3 1151.44   828.8 1157.55
   887.3  1193.3   906.8 1199.81   926.4    1211   965.4 1217.69  1033.6 1249.18
#Mann= 3 , 0 , 0
       0     .08       0   441.8    .045       0   456.8     .08       0
Bank Sta=441.8,456.8
XS Rating Curve= 0 ,0
Exp/Cntr=0.3,0.1

Type RM Length L Ch R = 1 ,5760.7  ,395.2,398.3,401.4
XS GIS Cut Line= 2
     1715612.651      296397.599     1715761.385      297298.271
#Sta/Elev= 30
       0 1168.39    49.1 1135.77    58.9 1135.58   127.6 1088.63   137.4 1087.59
   147.2 1081.76   206.1 1041.75   225.8 1035.22   284.7  999.68   343.6  977.82
   422.1  968.66   463.4  967.55   478.4  964.43     481   963.9   490.8  964.24
   500.6  969.52     530  994.18   539.9 1000.17   549.7 1002.12   618.4 1054.44
   628.2 1055.22   667.5 1083.79   696.9  1101.4   706.7 1101.94   775.4 1133.05
   785.3  1134.2   844.2 1155.93     854 1162.25   873.6 1168.71   912.9 1187.71
#Mann= 3 , 0 , 0
       0     .08       0   463.4    .045       0   478.4     .08       0
Bank Sta=463.4,478.4
XS Rating Curve= 0 ,0
Exp/Cntr=0.3,0.1

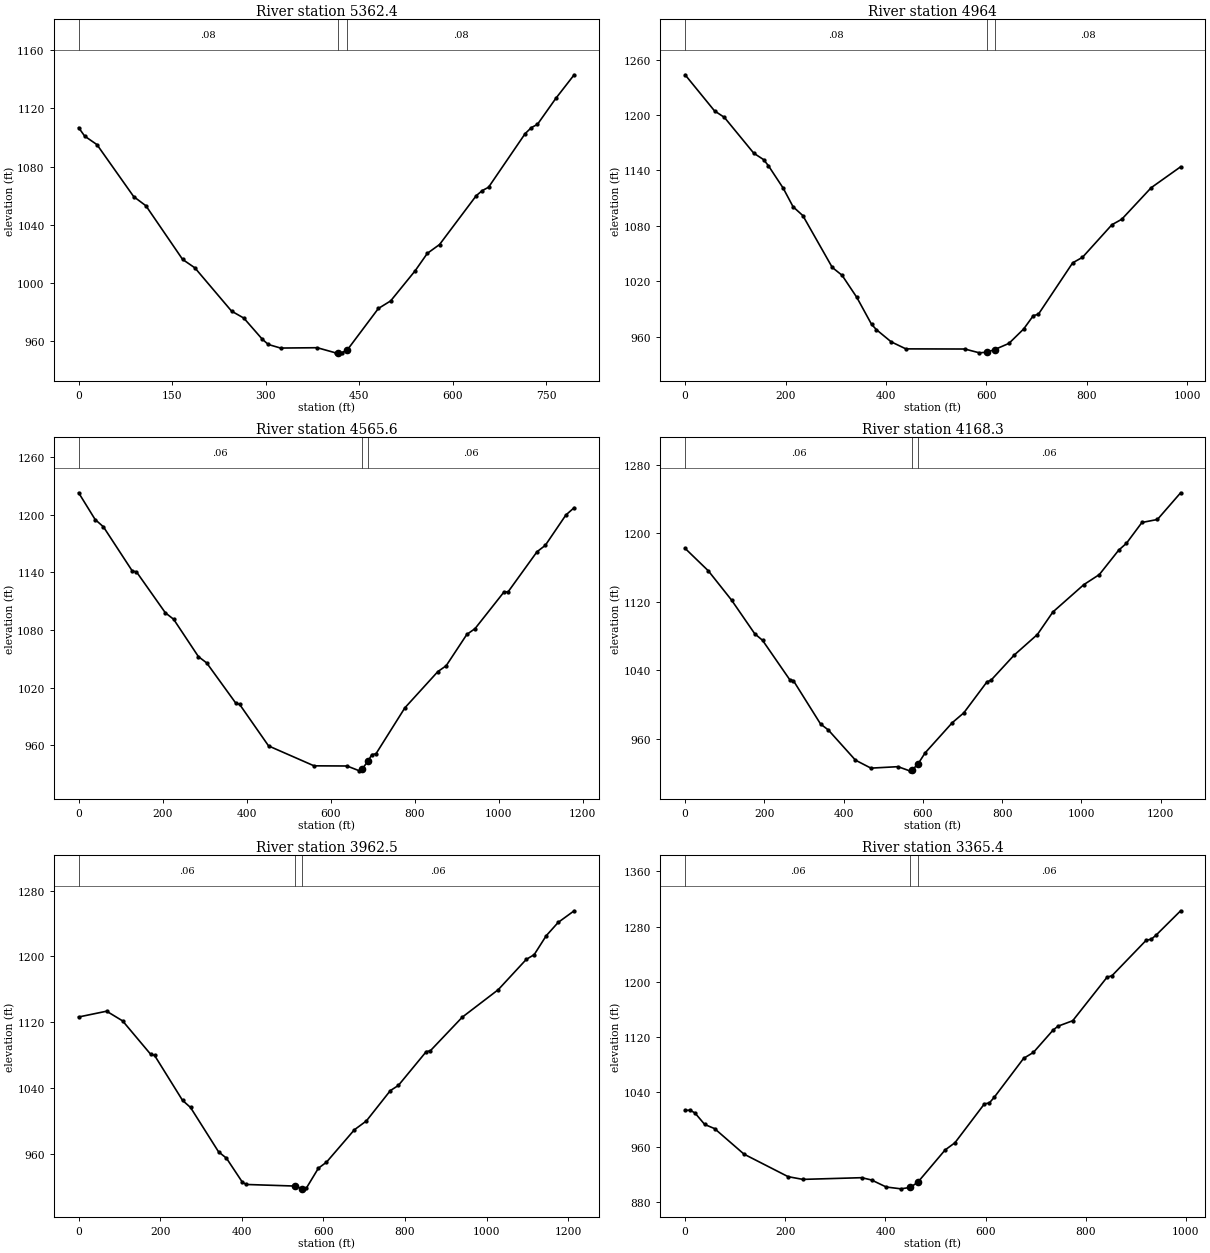
Type RM Length L Ch R = 1 ,5362.4  ,395.2,398.3,401.5
XS GIS Cut Line= 2
     1715305.433      296569.826     1715324.269      297364.789
#Sta/Elev= 30
       0  1106.7     9.8 1100.85    29.4 1095.06    88.4 1059.31     108 1053.03
   166.9 1016.16   186.5  1010.4   245.4  980.66   265.1  975.86   294.5  961.46
   304.3  957.75     324  955.28   382.9  955.51   412.3  951.99     416  952.02
   422.1  952.08     431  953.92     481  982.47   500.7  987.67   539.9 1008.31
   559.6 1020.36   579.2 1026.42   638.1    1060   647.9 1063.51   657.8 1065.76
   716.6 1102.64   726.5 1106.74   736.3 1108.99   765.7  1126.8   795.2 1143.04
#Mann= 3 , 0 , 0
       0     .08       0     416    .045       0     431     .08       0
Bank Sta=416,431
XS Rating Curve= 0 ,0
Exp/Cntr=0.3,0.1

Type RM Length L Ch R = 1 ,4964    ,395.3,398.5,401.6
XS GIS Cut Line= 2
     1714992.486      296415.149     1714879.044      297395.468
#Sta/Elev= 30
       0 1243.57    58.6 1204.46    78.2 1197.43   136.8  1158.6   156.3 1151.68
   166.1 1144.92   195.4 1120.71     215 1100.63   234.5 1091.02   293.1 1034.86
   312.7  1026.3     342  1002.4   371.3  973.26   381.1   967.4   410.4  954.27
   439.7  946.63   556.9  946.48   586.2  942.34   601.5  943.08   616.5  945.88
   644.9  952.56   674.2  968.13   693.7  982.75   703.5  984.04   771.9 1039.85
   791.4 1045.82   850.1 1081.15   869.6 1087.04   928.2 1121.22   986.9  1143.9
#Mann= 3 , 0 , 0
       0     .08       0   601.5    .045       0   616.5     .08       0
Bank Sta=601.5,616.5
XS Rating Curve= 0 ,0
Exp/Cntr=0.3,0.1

Type RM Length L Ch R = 1 ,4565.6  ,395.7,397.3,398.9
XS GIS Cut Line= 2
     1714716.347      296253.274     1714420.402      297395.468
#Sta/Elev= 30
       0 1223.03    39.3 1195.17      59 1187.57   127.8  1141.5   137.7 1140.65
   206.5 1097.96   226.2 1091.25   285.2 1052.32   304.8 1045.82   373.6 1004.21
   383.5 1002.44   452.3  959.26   560.5  938.53   639.1  938.36   668.6  933.31
   674.7  934.92   689.7  943.92   698.1  950.23     708  951.08   776.8  998.97
   855.4 1036.76   875.1 1042.78   924.3 1075.42   943.9  1081.5  1012.8 1119.67
  1022.6 1119.83  1091.4 1161.57  1111.1 1168.22  1160.2 1199.89  1179.9 1207.48
#Mann= 3 , 0 , 0
       0     .06       0   674.7    .045       0   689.7     .06       0
Bank Sta=674.7,689.7
XS Rating Curve= 0 ,0
Exp/Cntr=0.3,0.1

Type RM Length L Ch R = 1 ,4168.3  ,203.7,205.8,207.1
XS GIS Cut Line= 2
     1714478.065      296113.592     1714011.361      297273.713
#Sta/Elev= 30
       0  1182.6    58.6 1156.38   117.2 1122.18   175.8 1082.79   195.4 1075.17
   263.8  1029.3   273.5 1027.86   341.9   977.3   361.5  970.34   429.8  935.11
   468.9  925.76   537.3  927.46   566.6  922.59   572.1  923.21   587.1  930.19
   605.7  943.58   674.1   978.8   703.4   990.4     762 1026.73   771.8  1028.4
   830.4 1057.87     889 1081.93   928.1 1108.24  1006.2 1140.22  1045.3 1151.98
  1094.2 1180.52  1113.7 1188.54  1152.8 1212.86  1191.9 1216.38  1250.5 1247.59
#Mann= 3 , 0 , 0
       0     .06       0   572.1    .045       0   587.1     .06       0
Bank Sta=572.1,587.1
XS Rating Curve= 0 ,0
Exp/Cntr=0.3,0.1

Type RM Length L Ch R = 1 ,3962.5  ,601.3,597.1,593.6
XS GIS Cut Line= 2
     1714321.331      296029.992      1713832.73       297142.09
#Sta/Elev= 30
       0 1126.13    68.6 1133.18   107.8 1121.39   176.3 1080.92   186.1 1079.44
   254.7  1024.7   274.3 1016.06   342.9  962.17   362.4  954.32   401.6  924.98
   411.4  922.38   531.6  920.43   546.6   917.4   548.6  917.07   558.4  918.11
   587.8  942.24   607.4  949.42   675.9  988.91   705.3  999.65   764.1 1036.59
   783.7 1042.84   852.2 1084.07     862 1084.97   940.4 1125.91  1028.6 1159.35
  1097.2 1196.16  1116.7 1201.97  1146.1 1224.92  1175.5 1241.19  1214.7 1255.35
#Mann= 3 , 0 , 0
       0     .06       0   531.6    .045       0   546.6     .06       0
Bank Sta=531.6,546.6
XS Rating Curve= 0 ,0
Exp/Cntr=0.3,0.1

Type RM Length L Ch R = 1 ,3365.4  ,407.2,402.5,397.9
XS GIS Cut Line= 2
     1713643.153      295951.741     1713418.248      296915.248
#Sta/Elev= 30
       0 1013.22     9.8 1013.64    19.6 1009.64    39.2  992.86    58.8  986.92
   117.6  949.84   205.7  917.14   235.1   913.2   352.7  915.66   372.2  912.34
   401.6  902.13     431  899.48   449.5   901.6   464.5  908.95   519.2  955.94
   538.8  966.35   597.6 1022.79   607.4 1024.06   617.2 1032.29   675.9  1088.8
   695.5 1097.49   734.7 1129.79   744.5 1135.47   773.9 1143.41   842.5 1206.58
   852.3 1208.73   920.8 1260.32   930.6 1261.57   940.4 1267.64   989.4 1302.96
#Mann= 3 , 0 , 0
       0     .06       0   449.5    .045       0   464.5     .06       0
Bank Sta=449.5,464.5
XS Rating Curve= 0 ,0
Exp/Cntr=0.3,0.1

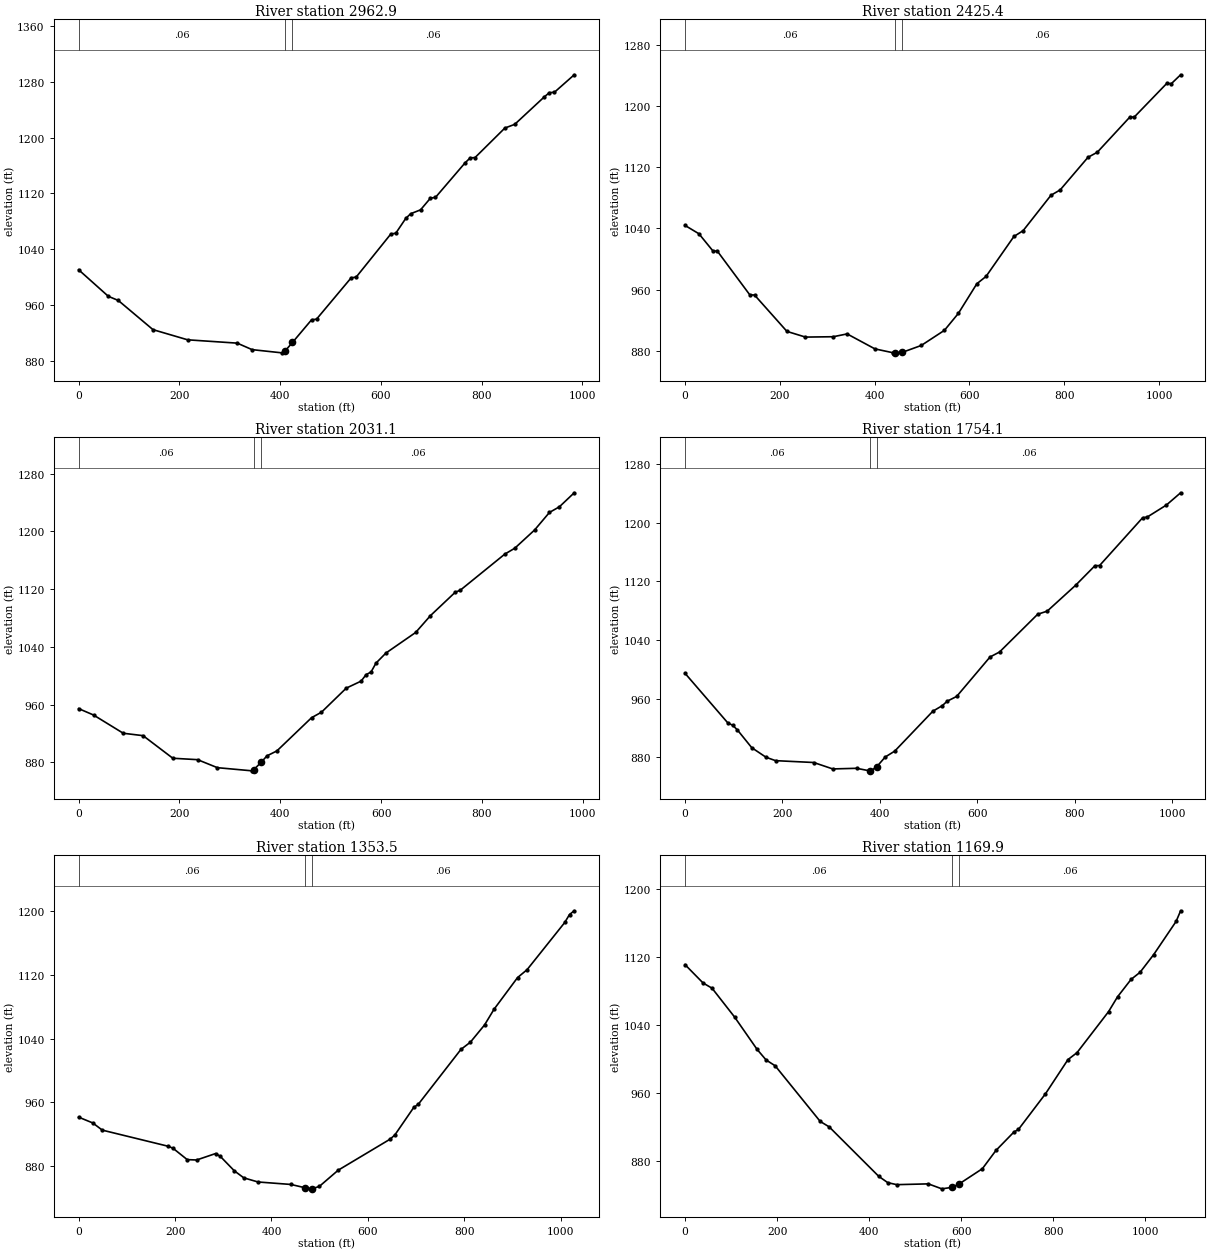
Type RM Length L Ch R = 1 ,2962.9  ,539.9,537.5,535.1
XS GIS Cut Line= 2
     1713163.272       295896.37     1713142.656      296879.813
#Sta/Elev= 30
       0 1010.67      59  972.62    78.7  966.72   147.6   924.9   216.4  910.34
   314.8  905.58   344.3  896.27   403.3  891.69   409.4  894.06   424.4  906.53
   462.3  938.96   472.2  939.93     541  999.19   550.8 1000.11   619.7 1061.93
   629.5    1063   649.2 1084.14     659 1090.91   678.7 1096.54   698.4 1113.36
   708.2 1114.26   767.2 1163.94   777.1 1170.84   786.9 1171.44     846 1213.65
   865.6 1218.97   924.6 1258.51   934.5 1264.39   944.3 1264.87   983.7 1289.96
#Mann= 3 , 0 , 0
       0     .06       0   409.4    .045       0   424.4     .06       0
Bank Sta=409.4,424.4
XS Rating Curve= 0 ,0
Exp/Cntr=0.3,0.1

Type RM Length L Ch R = 1 ,2425.4  ,403.4,394.3,385.2
XS GIS Cut Line= 2
     1712593.041      295866.784     1712685.695      296908.373
#Sta/Elev= 30
       0 1043.95    29.3 1033.09    58.6 1010.87    68.4 1010.26   136.8  953.26
   146.6  953.21     215  905.71   254.1  898.29   312.7  898.76     342  902.43
   400.7  882.88   439.8  877.74   443.7  877.88   458.7  878.46   498.4  887.36
   547.3  907.11   576.6  929.11   615.7  967.86   635.2  977.48   693.9 1029.52
   713.4 1037.16   772.1 1083.29   791.6 1090.35   850.2 1132.81   869.8 1139.41
   938.2 1185.11     948 1185.45  1016.4 1229.21  1026.2 1228.97  1045.7  1240.5
#Mann= 3 , 0 , 0
       0     .06       0   443.7    .045       0   458.7     .06       0
Bank Sta=443.7,458.7
XS Rating Curve= 0 ,0
Exp/Cntr=0.3,0.1

Type RM Length L Ch R = 1 ,2031.1  ,280.8,277,273.2
XS GIS Cut Line= 2
     1712092.842      296122.441     1712557.611      296988.507
#Sta/Elev= 30
       0  954.43    29.5  945.59    88.5   920.3   127.8  916.97   186.8  885.67
   235.9  883.71   275.2  872.61     344  868.23   347.6     870   362.6  880.52
   373.5  888.98   393.2  895.83     462  941.87   481.6  949.45   530.8  982.81
   560.2   992.5   570.1  1001.5   579.9 1005.11   589.7 1017.44   609.4 1031.39
   668.4 1059.91   697.8 1083.28     747 1115.72   756.8 1118.39   845.3 1168.52
     865 1176.62   904.3 1201.89   933.8 1226.24   953.4 1233.97   982.9 1253.44
#Mann= 3 , 0 , 0
       0     .06       0   347.6    .045       0   362.6     .06       0
Bank Sta=347.6,362.6
XS Rating Curve= 0 ,0
Exp/Cntr=0.3,0.1

Type RM Length L Ch R = 1 ,1754.1  ,402.4,400.7,398.9
XS GIS Cut Line= 2
     1711789.428       296277.52      1712417.59      297077.611
#Sta/Elev= 30
       0  994.49      88   926.7    97.8  923.67   107.6  917.19   136.9  893.06
   166.3  879.99   185.8  875.38   264.1  872.86   303.2  864.09   352.1  864.95
   378.8   861.5   381.5  861.49   393.8  867.29   410.8  880.32   430.4  888.39
   508.6  942.79   528.2  950.49     538  956.46   557.5  962.96     626 1016.77
   645.5 1023.57   723.8 1075.06   743.4 1079.31     802  1114.8   841.2 1141.19
   850.9 1141.54     939 1206.54   948.8  1207.7   987.9 1223.97  1017.2 1240.73
#Mann= 3 , 0 , 0
       0     .06       0   378.8    .045       0   393.8     .06       0
Bank Sta=378.8,393.8
XS Rating Curve= 0 ,0
Exp/Cntr=0.3,0.1

Type RM Length L Ch R = 1 ,1353.5  ,186.8,183.5,180.2
XS GIS Cut Line= 2
     1711409.472      296471.719     1712092.949      297239.435
#Sta/Elev= 30
       0  941.55    29.4  934.25      49  925.28     186     905   195.8   902.5
   225.2  888.28   244.7  887.82   283.9  895.86   293.7  892.44     323  874.18
   342.6   865.4     372  860.25   440.5  857.13   468.7  853.12   483.7  851.64
   499.2  854.68   538.4  875.04   646.1  913.96   655.9  919.24     695  953.68
   704.8  957.92   792.9 1026.49   812.5 1035.55   841.9 1057.17   861.5  1076.8
   910.4 1116.61     930 1126.41  1008.3 1185.73  1018.1 1195.68  1027.9 1200.36
#Mann= 3 , 0 , 0
       0     .06       0   468.7    .045       0   483.7     .06       0
Bank Sta=468.7,483.7
XS Rating Curve= 0 ,0
Exp/Cntr=0.3,0.1

Type RM Length L Ch R = 1 ,1169.9  ,625.2,620.4,615.6
XS GIS Cut Line= 2
     1711173.414      296599.099     1711997.818       297291.96
#Sta/Elev= 30
       0  1110.8    39.2 1089.27    58.7 1083.16   107.7 1049.31   156.6 1011.36
   176.2  998.94   195.8  992.16   293.7  926.88   313.3  920.45     421  862.42
   440.6  855.02   460.1   852.7   528.7  853.62     558  847.79     580  849.54
     595  853.33   646.1  871.42   675.5  892.78   714.7  914.47   724.5   917.5
   783.2  959.28   832.1  999.42   851.7 1007.52   920.2  1055.6   939.8 1073.06
   969.2 1093.51   988.8 1101.84  1018.2 1122.49  1067.1 1161.56  1076.9 1173.99
#Mann= 3 , 0 , 0
       0     .06       0     580    .045       0     595     .06       0
Bank Sta=580,595
XS Rating Curve= 0 ,0
Exp/Cntr=0.3,0.1

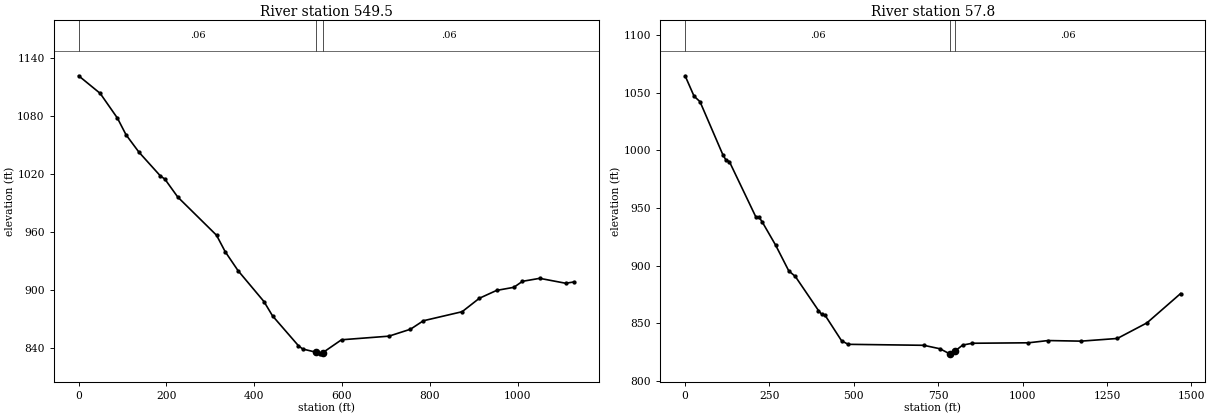
Type RM Length L Ch R = 1 ,549.5   ,499.8,491.7,483.7
XS GIS Cut Line= 2
     1710659.103      297070.551     1711654.819      297602.772
#Sta/Elev= 30
       0 1121.53    49.1 1103.35    88.4  1077.8     108 1060.59   137.4 1042.66
   186.5 1017.97   196.4 1014.86   225.8  996.32   314.2  956.84   333.8  939.96
   363.2  920.28   422.2  888.38   441.8  873.57   500.7  842.79   510.5  839.36
   541.4  835.95   549.8  834.36   556.4  835.62   598.9  848.88   706.9  852.61
     756  859.78   785.4  868.52   873.8  877.88     913  891.76   952.3  899.87
   991.6  903.07  1011.2  909.26  1050.5  912.34  1109.4  907.27    1129  908.62
#Mann= 3 , 0 , 0
       0     .06       0   541.4    .045       0   556.4     .06       0
Bank Sta=541.4,556.4
XS Rating Curve= 0 ,0
Exp/Cntr=0.3,0.1

Type RM Length L Ch R = 1 ,57.8    ,52.1,57.8,63.6
XS GIS Cut Line= 6
     1710529.651      297189.215     1710555.925       297235.27
     1710861.094      297770.192      1711041.74      297794.746
     1711620.509      297654.438     1711641.512      297649.347
#Sta/Elev= 30
       0  1064.5    26.5 1046.85    44.2 1042.04   111.7   996.2   121.4   991.3
   131.2  990.12   209.4  942.31   219.2  941.94     229   937.6   268.1  917.79
   307.2  895.42   326.7  890.56   395.2  861.06   404.9  857.72   414.7  856.97
   463.6  834.87   483.1  831.77   707.2  830.92   755.2  827.91     784  823.52
   785.8  823.66   800.8  826.14   822.4  831.12   851.2  832.69  1017.2  833.09
  1075.7  835.04  1173.4  834.52  1280.7  836.84  1368.6  850.37  1468.3   875.8
#Mann= 3 , 0 , 0
       0     .06       0   785.8    .045       0   800.8     .06       0
Bank Sta=785.8,800.8
XS Rating Curve= 0 ,0
Exp/Cntr=0.3,0.1

Chan Stop Cuts=-1
Use User Specified Reach Order=0
Composite Channel Slope=5